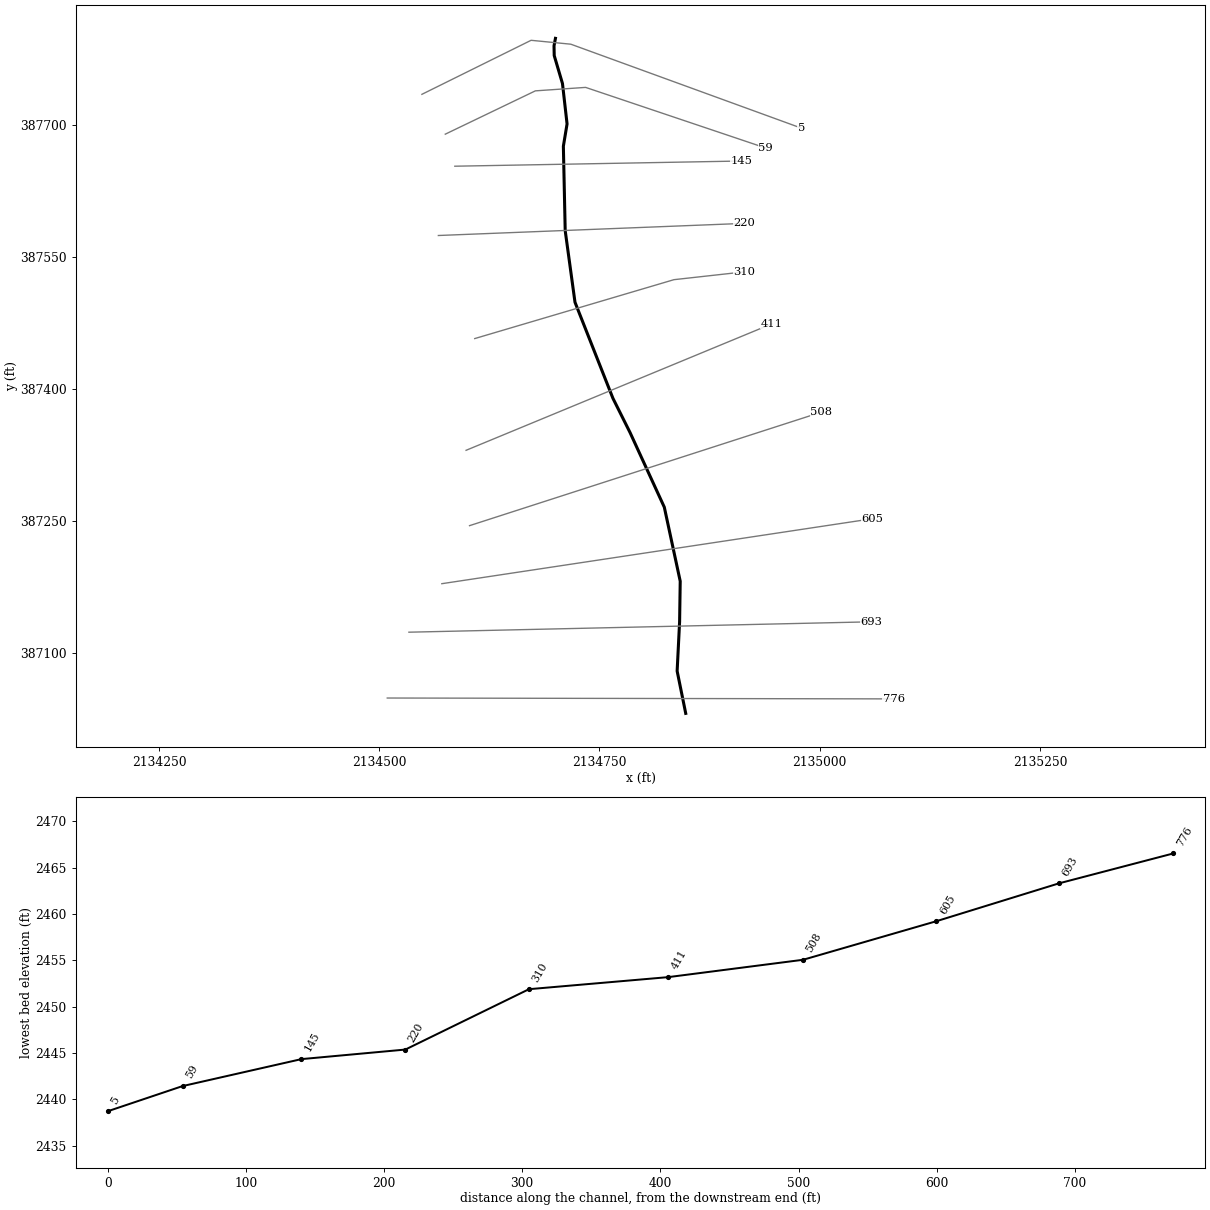
--- BEVERLYFK.prj (project) ---

Proj Title=BEVERLYFK
Current Plan=p01
Default Exp/Contr=0.3,0.1
English Units
Geom File=g01
Flow File=f01
Plan File=p01
Y Axis Title=Elevation
X Axis Title(PF)=Main Channel Distance
X Axis Title(XS)=Station
BEGIN DESCRIPTION:
Stream Name- Beverly Fork
Flood Zone: Zone A
Greenbrier County, WV
County-Wide Study
WVDHSEM-2018-3, Flood Risk Project
HEC-RAS Version: 5.0.7
General Notes:
For the Hydrology Regression was used.
END DESCRIPTION:
DSS Export Rating Curves= 0
DSS Export Rating Curve Sorted= 0
DSS Export Volume Flow Curves= 0
DXF Filename=A3a.
DXF OffsetX= 0
DXF OffsetY= 0
DXF ScaleX= 1
DXF ScaleY= 10

--- BEVERLYFK.p01 (plan) ---

Plan Title=Floodplain
Program Version=5.07
Short Identifier=Floodplain
Geom File=g01
Flow File=f01
Subcritical Flow
K Sum by GR= 0
Std Step Tol= 0.01
Critical Tol= 0.01
Num of Std Step Trials= 20
Max Error Tol= 0.3
Flow Tol Ratio= 0.001
Split Flow NTrial= 30
Split Flow Tol= 0.02
Split Flow Ratio= 0.02
Log Output Level= 0
Friction Slope Method= 1
Unsteady Friction Slope Method= 2
Unsteady Bridges Friction Slope Method= 1
Parabolic Critical Depth
Global Vel Dist= 0 , 0 , 0
Global Log Level= 0
CheckData=True
Encroach Param=-1 ,0,0, 0
Computation Interval=1MIN
Output Interval=1HOUR
Instantaneous Interval=1HOUR
Mapping Interval=1HOUR
Computation Time Step Use Courant=        0
Computation Time Step Use Time Series=    0
Computation Time Step Count To Double=0
Computation Time Step Max Doubling=0
Computation Time Step Max Halving=0
Computation Time Step Residence Courant=0
Run HTab= 0
Run UNet= 0
Run Sediment= 0
Run PostProcess= 0
Run WQNet= 0
Run RASMapper= 0
UNET Theta= 1
UNET Theta Warmup= 1
UNET ZTol= 0.02
UNET ZSATol= 0.02
UNET MxIter= 20
UNET Max Iter WO Improvement= 0
UNET MaxInSteps= 0
UNET DtIC= 0
UNET DtMin= 0
UNET MaxCRTS= 20
UNET WFStab= 2
UNET SFStab= 1
UNET WFX= 1
UNET SFX= 1
UNET 1D Methodology=Finite Difference
UNET DSS MLevel= 4
UNET Pardiso=0
UNET DZMax Abort= 100
UNET Use Existing IB Tables=-1
UNET Froude Reduction=False
UNET Froude Limit= 0.8
UNET Froude Power= 4
UNET D1 Cores= 0
UNET D2 Coriolis=0
UNET D2 Cores= 0
UNET D2 Theta= 1
UNET D2 Theta Warmup= 1
UNET D2 Z Tol= 0.01
UNET D2 Volume Tol= 0.01
UNET D2 Max Iterations= 20
UNET D2 Equation= 0
UNET D2 RampUpFraction=0.1
UNET D2 TimeSlices= 1
UNET D2 BCVolumeCheck=0
UNET D1D2 MaxIter= 0
UNET D1D2 ZTol=0.01
UNET D1D2 QTol=0.1
UNET D1D2 MinQTol=1
Write IC File= 0
Write IC File at Fixed DateTime=0
Write IC File at Sim End=0
Echo Input=False
Echo Parameters=False
Echo Output=False
Write Detailed= 0
HDF Write Warmup=0
HDF Write Time Slices=0
HDF Flush=0
HDF Face Node Velocities=0
HDF Compression= 1
HDF Chunk Size= 1
HDF Spatial Parts= 1
HDF Use Max Rows=0
HDF Fixed Rows= 1
Calibration Method= 0
Calibration Iterations= 20
Calibration Max Change=0.05
Calibration Tolerance=0.2
Calibration Maximum=1.5
Calibration Minimum=0.5
Calibration Optimization Method= 1
WQ AD Non Conservative
WQ ULTIMATE=-1
WQ Max Comp Step=1HOUR
WQ Output Interval=15MIN
WQ Output Selected Increments= 0
WQ Output face flow=0
WQ Output face velocity=0
WQ Output face area=0
WQ Output face dispersion=0
WQ Output cell volume=0
WQ Output cell surface area=0
WQ Output cell continuity=0
WQ Output cumulative cell continuity=0
WQ Output face conc=0
WQ Output face dconc_dx=0
WQ Output face courant=0
WQ Output face peclet=0
WQ Output face adv mass=0
WQ Output face disp mass=0
WQ Output cell mass=0
WQ Output cell source sink temp=0
WQ Output nsm pathways=0
WQ Output nsm derived pathways=0
WQ Output MaxMinRange=-1
WQ Daily Max Min Mean=-1
WQ Daily Range=0
WQ Daily Time=0
WQ Create Restart=0
WQ Fixed Restart=0
WQ System Summary=0
WQ Write To DSS=0
WQ Use Fixed Temperature=0
Sorting and Armoring Iterations= 10
XS Update Threshold= 0.02
Bed Roughness Predictor= 0
Hydraulics Update Threshold= 0.02
Energy Slope Method= 1
Volume Change Method= 1
Sediment Retention Method= 0
XS Weighting Method= 0
Number of US Weighted Cross Sections= 1
Number of DS Weighted Cross Sections= 1
Upstream XS Weight=0
Main XS Weight=1
Downstream XS Weight=0
Number of DS XS's Weighted with US Boundary= 1
Upstream Boundary Weight= 1
Weight of XSs Associated with US Boundary= 0
Number of US XS's Weighted with DS Boundary= 1
Downstream Boundary Weight= 0.5
Weight of XSs Associated with DS Boundary= 0.5
Percentile Method= 0
Sediment Output Level= 3
Mass or Volume Output= 0
Output Increment Type= 1
Profile and TS Output Increment= 1
XS Output Flag= 0
XS Output Increment= 10
Write Gradation File= 0
Read Gradation Hotstart= 0
Write HDF5 File= 1
Write Binary Output= 1
Write DSS Sediment File= 0
SV Curve= 0
Specific Gage Flag= 0

--- BEVERLYFK.f01 (steady flow) ---

Flow Title=Flow
Program Version=5.07
Number of Profiles= 6
Profile Names=f1p,f10p,f4p,f2p,f02p,f1pplus
River Rch & RM=BEVERLYFK,Main            ,776
     323     167     225     272     456     478
River Rch & RM=BEVERLYFK,Main            ,693
     537     283     377     454     751     794
Boundary for River Rch & Prof#=BEVERLYFK,Main            , 1
Up Type= 0
Dn Type= 3
Dn Slope=0.045649
Boundary for River Rch & Prof#=BEVERLYFK,Main            , 2
Up Type= 0
Dn Type= 3
Dn Slope=0.045649
Boundary for River Rch & Prof#=BEVERLYFK,Main            , 3
Up Type= 0
Dn Type= 3
Dn Slope=0.045649
Boundary for River Rch & Prof#=BEVERLYFK,Main            , 4
Up Type= 0
Dn Type= 3
Dn Slope=0.045649
Boundary for River Rch & Prof#=BEVERLYFK,Main            , 5
Up Type= 0
Dn Type= 3
Dn Slope=0.045649
Boundary for River Rch & Prof#=BEVERLYFK,Main            , 6
Up Type= 0
Dn Type= 3
Dn Slope=0.045649
Boundary for River Rch & Prof#=BOGGSRN,Main            , 1
Up Type= 0
Dn Type= 3
Dn Slope=0.043074
Boundary for River Rch & Prof#=BOGGSRN,Main            , 2
Up Type= 0
Dn Type= 3
Dn Slope=0.043074
Boundary for River Rch & Prof#=BOGGSRN,Main            , 3
Up Type= 0
Dn Type= 3
Dn Slope=0.043074
Boundary for River Rch & Prof#=BOGGSRN,Main            , 4
Up Type= 0
Dn Type= 3
Dn Slope=0.043074
Boundary for River Rch & Prof#=BOGGSRN,Main            , 5
Up Type= 0
Dn Type= 3
Dn Slope=0.043074
Boundary for River Rch & Prof#=BOGGSRN,Main            , 6
Up Type= 0
Dn Type= 3
Dn Slope=0.043074
Boundary for River Rch & Prof#=DRYRN,Main            , 1
Up Type= 0
Dn Type= 3
Dn Slope=0.021282
Boundary for River Rch & Prof#=DRYRN,Main            , 2
Up Type= 0
Dn Type= 3
Dn Slope=0.021282
Boundary for River Rch & Prof#=DRYRN,Main            , 3
Up Type= 0
Dn Type= 3
Dn Slope=0.021282
Boundary for River Rch & Prof#=DRYRN,Main            , 4
Up Type= 0
Dn Type= 3
Dn Slope=0.021282
Boundary for River Rch & Prof#=DRYRN,Main            , 5
Up Type= 0
Dn Type= 3
Dn Slope=0.021282
Boundary for River Rch & Prof#=DRYRN,Main            , 6
Up Type= 0
Dn Type= 3
Dn Slope=0.021282
Boundary for River Rch & Prof#=PNTHRCMPCK,Main            , 1
Up Type= 0
Dn Type= 3
Dn Slope=0.02712
Boundary for River Rch & Prof#=PNTHRCMPCK,Main            , 2
Up Type= 0
Dn Type= 3
Dn Slope=0.02712
Boundary for River Rch & Prof#=PNTHRCMPCK,Main            , 3
Up Type= 0
Dn Type= 3
Dn Slope=0.02712
Boundary for River Rch & Prof#=PNTHRCMPCK,Main            , 4
Up Type= 0
Dn Type= 3
Dn Slope=0.02712
Boundary for River Rch & Prof#=PNTHRCMPCK,Main            , 5
Up Type= 0
Dn Type= 3
Dn Slope=0.02712
Boundary for River Rch & Prof#=PNTHRCMPCK,Main            , 6
Up Type= 0
Dn Type= 3
Dn Slope=0.02712
Boundary for River Rch & Prof#=RCKCMPRN,Main            , 1
Up Type= 0
Dn Type= 3
Dn Slope=0.013802
Boundary for River Rch & Prof#=RCKCMPRN,Main            , 2
Up Type= 0
Dn Type= 3
Dn Slope=0.013802
Boundary for River Rch & Prof#=RCKCMPRN,Main            , 3
Up Type= 0
Dn Type= 3
Dn Slope=0.013802
Boundary for River Rch & Prof#=RCKCMPRN,Main            , 4
Up Type= 0
Dn Type= 3
Dn Slope=0.013802
Boundary for River Rch & Prof#=RCKCMPRN,Main            , 5
Up Type= 0
Dn Type= 3
Dn Slope=0.013802
Boundary for River Rch & Prof#=RCKCMPRN,Main            , 6
Up Type= 0
Dn Type= 3
Dn Slope=0.013802
Boundary for River Rch & Prof#=ROBBINSRN,Main            , 1
Up Type= 0
Dn Type= 3
Dn Slope=0.010317
Boundary for River Rch & Prof#=ROBBINSRN,Main            , 2
Up Type= 0
Dn Type= 3
Dn Slope=0.010317
Boundary for River Rch & Prof#=ROBBINSRN,Main            , 3
Up Type= 0
Dn Type= 3
Dn Slope=0.010317
Boundary for River Rch & Prof#=ROBBINSRN,Main            , 4
Up Type= 0
Dn Type= 3
Dn Slope=0.010317
Boundary for River Rch & Prof#=ROBBINSRN,Main            , 5
Up Type= 0
Dn Type= 3
Dn Slope=0.010317
Boundary for River Rch & Prof#=ROBBINSRN,Main            , 6
Up Type= 0
Dn Type= 3
Dn Slope=0.010317
Boundary for River Rch & Prof#=SPRINGCKT3,Main            , 1
Up Type= 0
Dn Type= 3
Dn Slope=0.016207
Boundary for River Rch & Prof#=SPRINGCKT3,Main            , 2
Up Type= 0
Dn Type= 3
Dn Slope=0.016207
Boundary for River Rch & Prof#=SPRINGCKT3,Main            , 3
Up Type= 0
Dn Type= 3
Dn Slope=0.016207
Boundary for River Rch & Prof#=SPRINGCKT3,Main            , 4
Up Type= 0
Dn Type= 3
Dn Slope=0.016207
Boundary for River Rch & Prof#=SPRINGCKT3,Main            , 5
Up Type= 0
Dn Type= 3
Dn Slope=0.016207
Boundary for River Rch & Prof#=SPRINGCKT3,Main            , 6
Up Type= 0
Dn Type= 3
Dn Slope=0.016207
DSS Import GetInterval= 0
DSS Import GetPeak= 0
DSS Import FillOption= 0

--- BEVERLYFK.g01 (geometry) ---

Geom Title=Geometry
Program Version=5.07

River Reach=BEVERLYFK       ,Main
Reach XY= 30
2134847.92903405387031.5921410622134838.20694064387079.508711889
 2134838.1898803387079.8653384752134840.98449413387135.758599401
2134841.67904656387181.5918410572134823.62330839387265.619888231
2134784.73460664387350.3421597332134783.34582989387353.120041311
2134781.95672506 387355.897594812134779.17917155 387361.45335798
2134777.79006672387364.2309114782134775.01251322387369.786674649
 2134770.8455268387378.119663224 2134768.0679733387383.675426394
2134766.67886847387386.4529798922134765.29009172 387389.23086147
 2134750.9380863387425.5733084832134748.54635881 387431.63038297
2134744.95811139387440.7159947312134742.56638388387446.773397312
2134738.97813647387455.8590090572134732.99848963387471.001695305
2134722.23440355387498.2585305572134711.12353338387579.508696139
2134709.04020423387675.3418378082134713.23442155387700.689228058
2134708.02609864387746.5224697292134698.65111738387778.293403566
2134698.43556663387789.2963343112134700.05268939387797.827813312

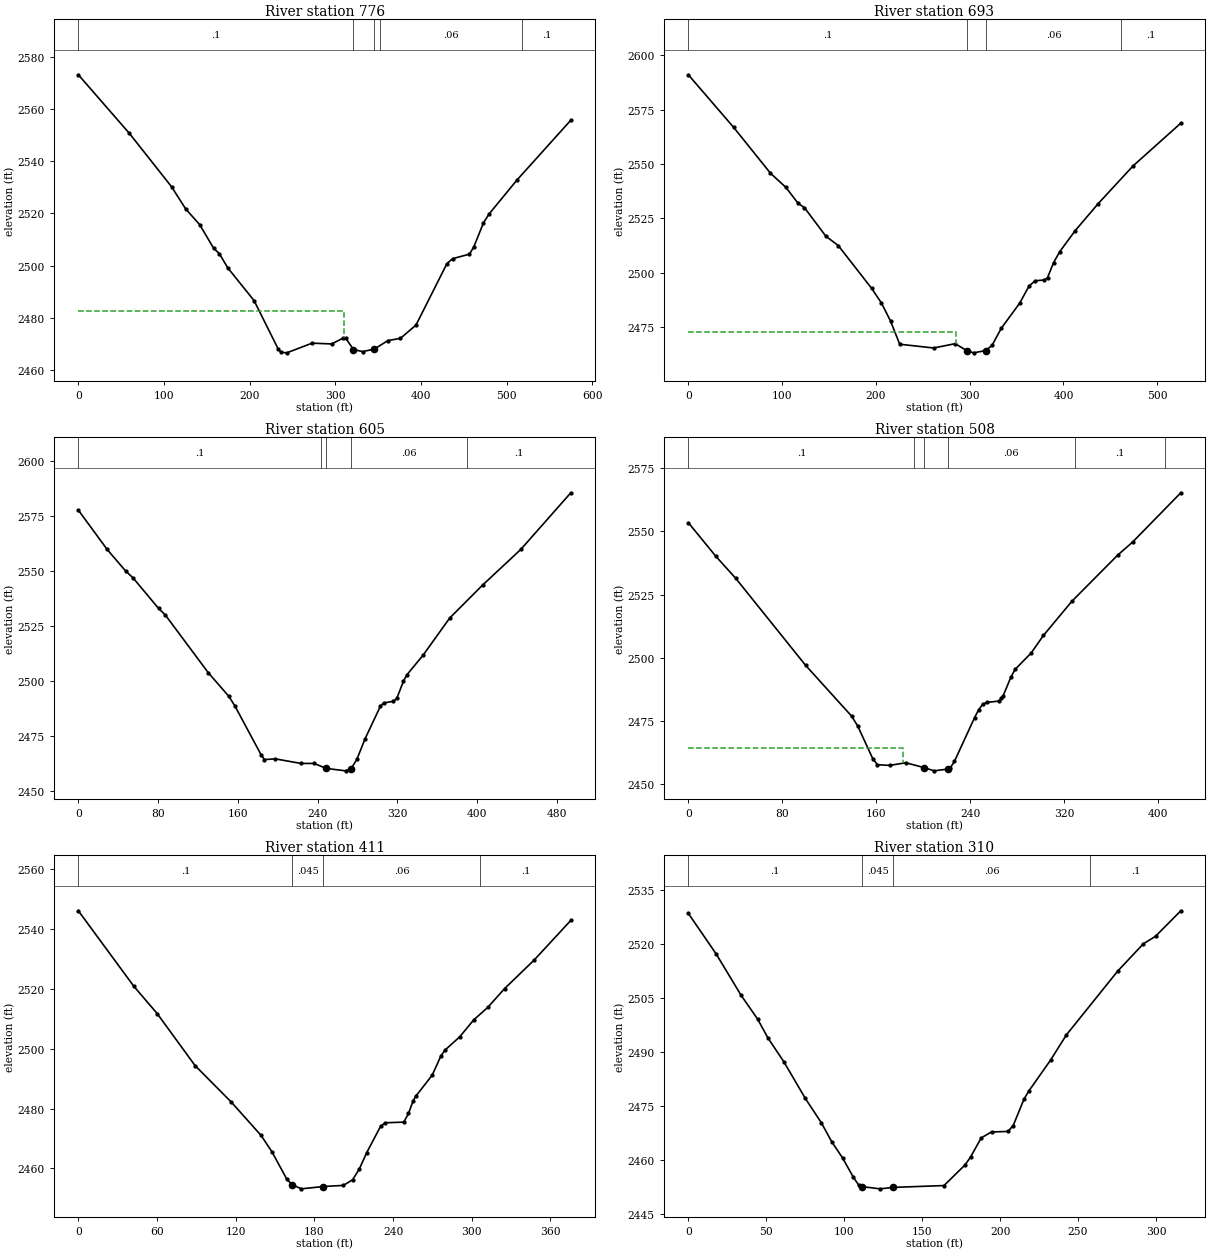
Type RM Length L Ch R = 1 ,776     ,82.5,82.9,83.1
XS GIS Cut Line= 2
2134509.13902922387049.020583898 2135084.2838763 387048.03731814
#Sta/Elev= 30
       0 2573.16    59.7 2550.65   108.9  2530.2   125.3 2521.74   141.7 2515.68
   158.1 2506.58   164.7 2504.55   174.5 2499.11   205.2 2486.57   233.6 2467.86
   236.8 2466.74   243.4 2466.53   272.9 2470.24   295.9 2469.94     309 2472.16
   312.3 2472.11  321.292467.794     332 2467.01  345.582467.963   361.5 2471.23
   376.1 2472.09   394.3 2477.18   430.4 2500.73     437 2502.64   456.7 2504.37
   461.7 2507.07   473.1 2516.37   479.6 2519.76   512.4 2532.87   575.1 2555.74
#Mann= 5 ,-1 , 0
       0      .1       0  321.29    .045       0  345.58      .1       0
  351.91     .06       0  518.12      .1       0
#XS Ineff= 2 , 0
          310.36 2482.46
Permanent Ineff=
       F       F
Bank Sta=321.29,345.58
XS Rating Curve= 0 ,0
Exp/Cntr=0.3,0.1

Type RM Length L Ch R = 1 ,693     ,87.1,88.7,89.7
XS GIS Cut Line= 2
 2134533.7180483387123.7402507222135058.72191955387135.538127393
#Sta/Elev= 30
       0 2590.97    48.2 2566.89    87.6 2545.77     104 2539.28   117.2 2531.87
   123.7 2530.02   146.7 2516.83   159.8 2512.58   195.5 2492.89   205.8 2486.25
   215.6 2477.91   225.4 2467.25   261.5 2465.53   284.5  2467.5  297.062464.296
   304.2  2463.3  317.112464.346   323.9 2466.76   333.7 2474.58   353.3 2486.09
   363.3 2493.98   369.8 2496.39   379.7 2496.76     383 2497.82   389.5 2504.77
   396.1  2509.8   412.5  2519.4     437  2531.8   474.1 2549.08   525.1 2568.75
#Mann= 4 ,-1 , 0
       0      .1       0  297.06    .045       0  317.11     .06       0
   461.4      .1       0
#XS Ineff= 2 , 0
          285.57 2473.02
Permanent Ineff=
       F       F
Bank Sta=297.06,317.11
XS Rating Curve= 0 ,0
Exp/Cntr=0.3,0.1

Type RM Length L Ch R = 1 ,605     ,93.9,96.5,97.8
XS GIS Cut Line= 2
2134571.07788172 387178.796899142135059.70485722387252.533300221
#Sta/Elev= 30
       0 2577.49    28.8 2559.72    47.5 2549.85    54.8  2546.8    80.6 2532.87
    87.3 2529.91   130.4 2503.73     151 2493.02     157 2488.72   183.5 2466.42
   186.8 2464.34   197.8 2464.64   223.3 2462.59   236.6 2462.57  248.722460.332
   268.1 2459.22  273.752460.176   279.6 2464.54   287.7 2473.74     303 2488.42
   306.3    2490   316.2 2490.79   319.6 2492.12   326.2 2499.84   329.5 2502.67
   346.1 2511.78   372.6 2528.51   405.8 2543.55     444 2559.67   494.2 2585.37
#Mann= 5 ,-1 , 0
       0      .1       0  243.56     .06       0  248.72    .045       0
  273.75     .06       0   389.7      .1       0
Bank Sta=248.72,273.75
XS Rating Curve= 0 ,0
Exp/Cntr=0.3,0.1

Type RM Length L Ch R = 1 ,508     ,97,97.6,98.4
XS GIS Cut Line= 2
 2134602.5387768387244.6681584722135001.69906773387373.461207971
#Sta/Elev= 30
       0  2553.5    23.2 2540.29    40.4  2531.4    99.9  2496.9     139 2476.79
   144.2 2472.89   157.2 2459.76   161.1 2457.49   171.4 2457.22   185.2 2458.27
  201.072456.301   209.3 2455.06  221.212455.771   223.1 2456.23   226.6 2458.79
   243.8 2476.18   247.3 2479.34   250.7 2481.41   254.1 2482.19   264.5 2482.74
   266.7  2483.8   267.9 2484.58   274.8 2492.33   278.3  2495.3   292.1 2501.87
   302.4 2508.75   326.5 2522.24   365.7 2540.64   378.3 2545.77   419.4 2565.35
#Mann= 6 ,-1 , 0
       0      .1       0  192.54     .06       0  201.07    .045       0
  221.21     .06       0  328.97      .1       0   405.9      .1       0
#XS Ineff= 2 , 0
          183.08 2464.27
Permanent Ineff=
       F       F
Bank Sta=201.07,221.21
XS Rating Curve= 0 ,0
Exp/Cntr=0.3,0.1

Type RM Length L Ch R = 1 ,411     ,101.9,100.8,99.7
XS GIS Cut Line= 2
2134598.60604189387330.2024362242134945.65915355387473.742831558
#Sta/Elev= 30
       0 2546.05    42.3 2520.84    60.1 2511.74      89 2494.36   116.7 2482.14
   139.3 2471.06   147.7 2465.53   159.1 2456.33  163.292454.529   170.1 2453.19
  186.742453.959   202.1 2454.34   209.2 2456.22   214.3 2459.82   219.8 2465.17
   230.5 2474.08     234 2475.25   248.2 2475.47   251.8 2478.36   255.3 2482.56
   257.3 2484.09   269.9 2491.17   276.6 2497.66   279.9 2499.63   290.9 2503.97
   301.5  2509.6   312.2 2513.76   325.1 2520.07   347.7 2529.62   375.6 2542.84
#Mann= 4 ,-1 , 0
       0      .1       0  163.29    .045       0  186.74     .06       0
   306.4      .1       0
Bank Sta=163.29,186.74
XS Rating Curve= 0 ,0
Exp/Cntr=0.3,0.1

Type RM Length L Ch R = 1 ,310     ,91.9,89.5,87
XS GIS Cut Line= 3
2134608.43771514387457.0292823172134834.56291905387523.883807391
2134914.19825847387532.731886804
#Sta/Elev= 30
       0  2528.6      18 2517.21    33.8 2505.81    44.4 2499.19    51.1 2493.89
    61.3 2487.26      75  2477.1    85.3 2470.31    92.1 2464.92      99 2460.46
   105.8 2455.16   109.2 2453.01  111.422452.506   122.9 2451.89   131.52452.294
     164  2452.8   177.6 2458.59   181.1  2460.8   187.9 2466.09   194.5 2467.73
     205 2467.87   208.4 2469.51   215.3 2476.86   218.6 2479.25   232.4 2487.76
   242.4 2494.69   275.4 2512.51   291.9 2520.13   299.7 2522.21   315.9 2529.32
#Mann= 4 ,-1 , 0
       0      .1       0  111.42    .045       0   131.5     .06       0
  257.69      .1       0
Bank Sta=111.42,131.5
XS Rating Curve= 0 ,0
Exp/Cntr=0.3,0.1

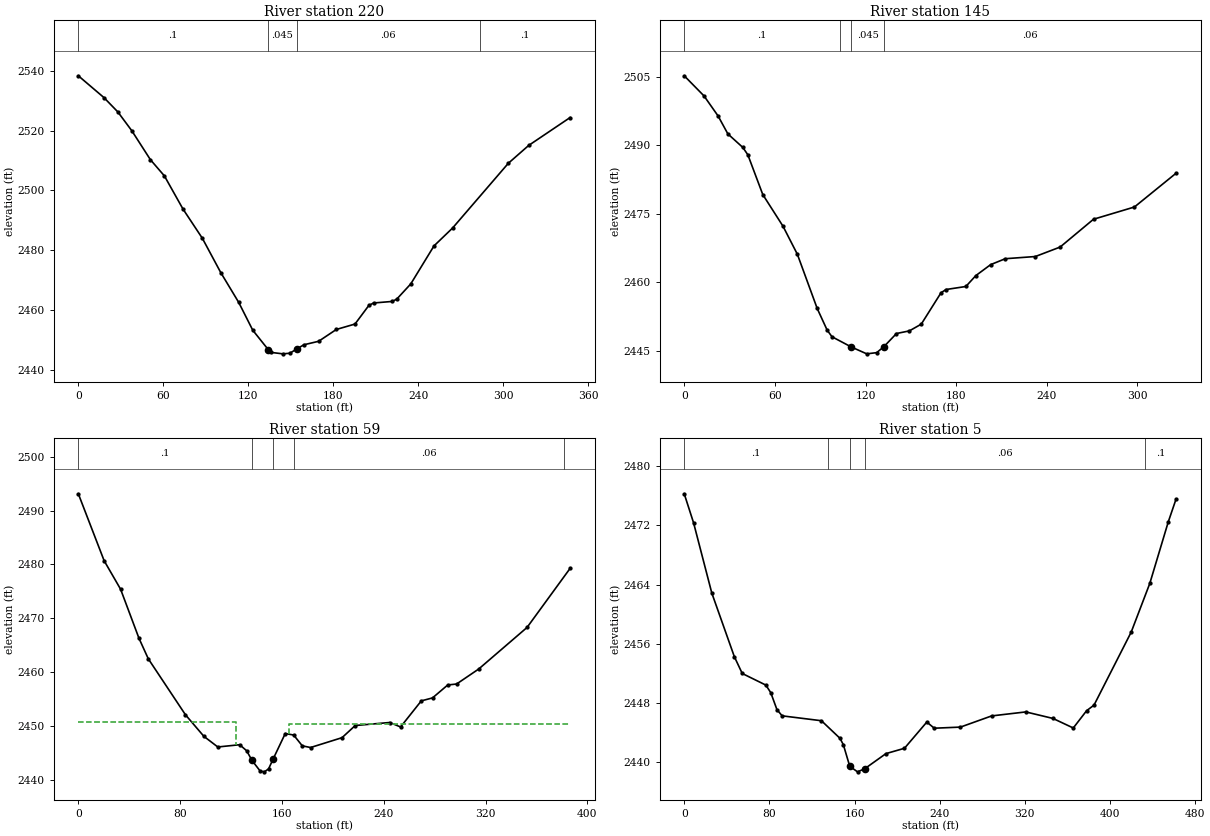
Type RM Length L Ch R = 1 ,220     ,75.5,75.2,75
XS GIS Cut Line= 2
 2134567.1451468387574.0244551452134914.19825847387587.788535222
#Sta/Elev= 30
       0 2538.29    18.1    2531    27.9 2526.22    37.8 2519.91    50.9 2510.26
    60.8 2504.83    73.9 2493.78    87.6 2483.99   100.6 2472.53   113.3 2462.55
   123.2 2453.27  134.092446.821   136.3 2445.85   144.4 2445.38   149.4 2445.58
  154.112446.971   159.3 2448.41   169.7 2449.57   182.2 2453.52   195.4 2455.34
   205.2 2461.56   208.5 2462.37   221.7 2462.89   224.9 2463.67   234.8 2468.75
   251.2 2481.45   264.3 2487.41   303.7 2509.06   318.1 2515.03   347.3 2524.33
#Mann= 4 ,-1 , 0
       0      .1       0  134.09    .045       0  154.11     .06       0
  283.33      .1       0
Bank Sta=134.09,154.11
XS Rating Curve= 0 ,0
Exp/Cntr=0.3,0.1

Type RM Length L Ch R = 1 ,145     ,85.7,86.1,86.3
XS GIS Cut Line= 2
2134585.82522756 387652.676856892134911.24878931387658.575795233
#Sta/Elev= 30
       0 2505.21    13.1  2500.8    22.4 2496.42    28.9 2492.48    38.8 2489.52
    42.1 2487.92      52 2479.21    65.4 2472.27    74.9 2466.13      88 2454.29
    94.6 2449.54    97.8 2448.09  110.662445.837   120.8 2444.35   127.4 2444.61
  132.182445.927   140.5  2448.8     149 2449.37   156.9 2450.85     170 2457.73
   173.3 2458.43   186.4 2459.09     193 2461.47   202.8 2463.87   212.5 2465.17
   232.4 2465.65   248.8 2467.72   270.9 2473.81     298 2476.49   325.5 2483.87
#Mann= 4 ,-1 , 0
       0      .1       0  103.24     .06       0  110.66    .045       0
  132.18     .06       0
Bank Sta=110.66,132.18
XS Rating Curve= 0 ,0
Exp/Cntr=0.3,0.1

Type RM Length L Ch R = 1 ,59      ,55.6,54.1,53.9
XS GIS Cut Line= 4
2134575.01028855387689.0534245672134677.25844364387738.211134642
2134734.28129546 387742.143541472134938.77694947387673.322812974
#Sta/Elev= 30
       0 2493.12    20.3 2480.67    33.2 2475.39    47.7 2466.24      55 2462.44
    84.2 2452.04    98.7 2448.03   109.6 2446.06   126.8 2446.48   132.3 2445.35
  136.432443.573   142.9 2441.58   146.2 2441.44   149.5 2441.99  153.212443.891
   162.6 2448.56   169.2 2448.28     176 2446.27   182.5 2445.96   207.2 2447.79
   217.6 2450.05   244.7 2450.61   253.2 2449.78   269.5 2454.63   278.3 2455.18
   290.3 2457.59   297.2 2457.76   314.6 2460.55   352.6 2468.28   386.4 2479.25
#Mann= 5 ,-1 , 0
       0      .1       0  136.43    .045       0  153.21      .1       0
  169.56     .06       0  381.35      .1       0
#XS Ineff= 2 ,-1
       0   123.6 2450.63  165.93  386.37 2450.33
Permanent Ineff=
       F       F
Bank Sta=136.43,153.21
XS Rating Curve= 0 ,0
Exp/Cntr=0.3,0.1

Type RM Length L Ch R = 1 ,5       ,18.06,17,17.25
XS GIS Cut Line= 4
2134548.46539414387734.2783997212134672.39969743387795.596128817
2134717.51016368387791.1728629812134979.08625205387695.935628638
#Sta/Elev= 30
       0 2476.27     8.8 2472.34    25.9 2462.87    47.1 2454.27    54.5 2452.01
    76.7 2450.44    81.3 2449.42    87.1 2447.13      92 2446.29   128.9 2445.63
   146.3 2443.26   149.5 2442.39   155.5 2439.48   162.8 2438.73  169.48 2439.14
   189.5 2441.19   206.9 2441.91   227.9 2445.45   234.9 2444.62   259.5 2444.77
   288.8 2446.28   320.9 2446.82   346.4 2445.94   365.5 2444.65     378 2446.98
     385 2447.74   419.9 2457.59   437.4 2464.17   454.8  2472.5     462 2475.53
#Mann= 5 ,-1 , 0
       0      .1       0  134.78     .06       0   155.5    .045       0
  169.48     .06       0  432.94      .1       0
Bank Sta=155.5,169.48
XS Rating Curve= 0 ,0
Exp/Cntr=0.3,0.1
LCMann Table=0

Chan Stop Cuts=-1
Use User Specified Reach Order=0
Composite Channel Slope=5